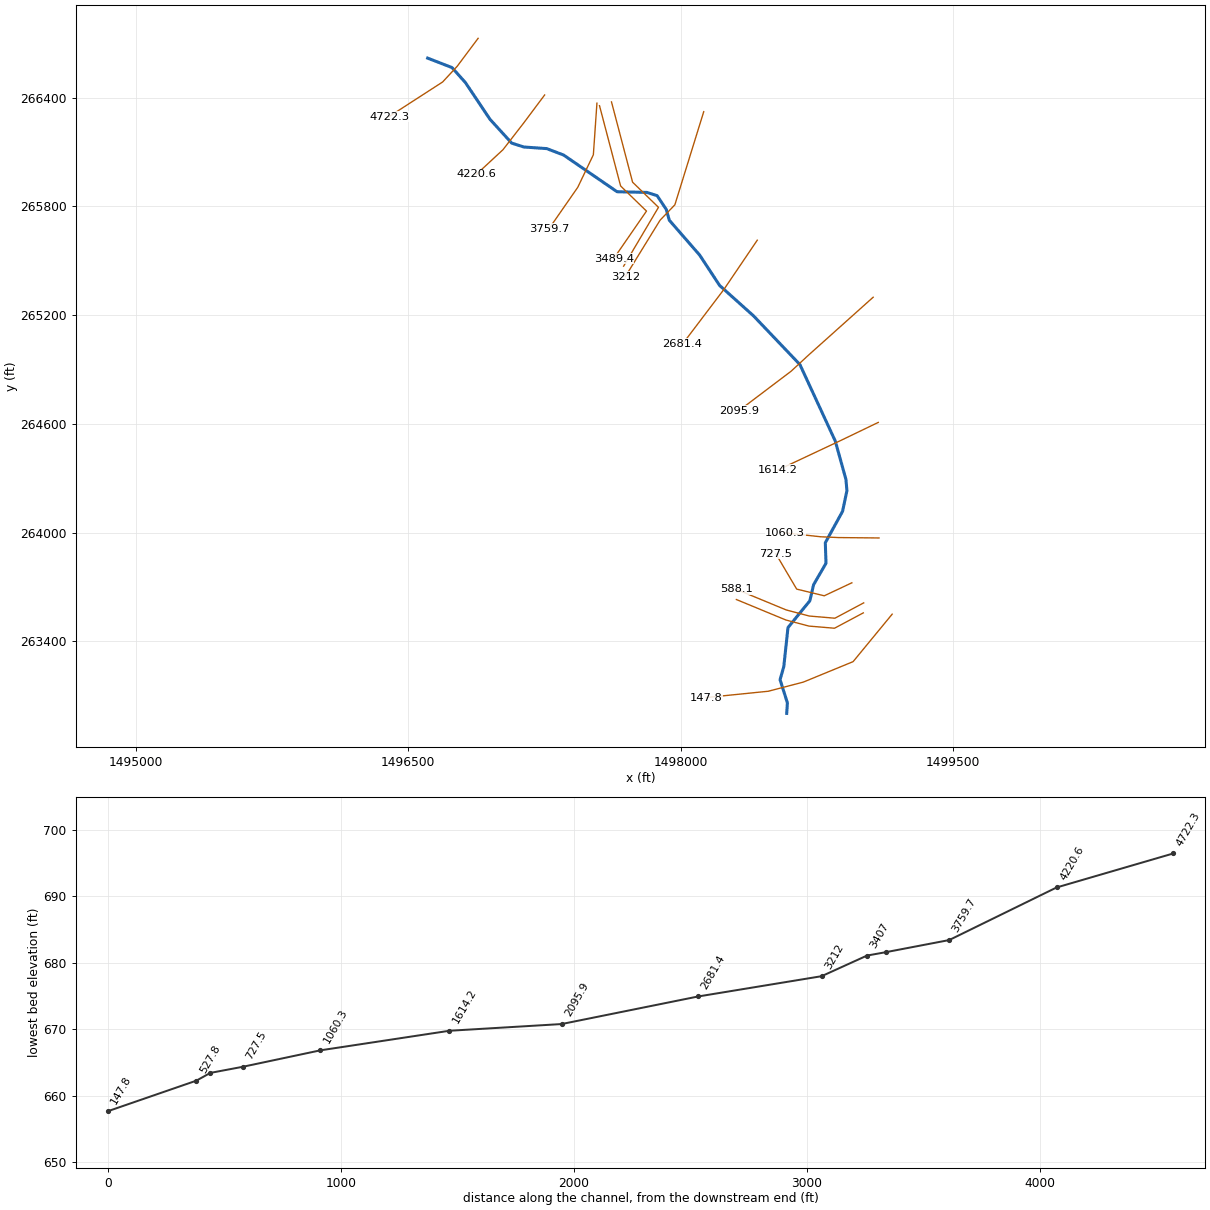
--- BGRN.prj (project) ---

Proj Title=BGRN
Current Plan=p01
Default Exp/Contr=0,0
English Units
Geom File=g01
Flow File=f01
Plan File=p01
BEGIN DESCRIPTION:
END DESCRIPTION:
DSS Export Rating Curves= 0
DSS Export Rating Curve Sorted= 0
DSS Export Volume Flow Curves= 0
DXF OffsetX= 0
DXF OffsetY= 0
DXF ScaleX= 0
DXF ScaleY= 0

--- BGRN.p01 (plan) ---

Plan Title=Floodplain
Program Version=4.00
Geom File=g01
Flow File=f01
K Sum by GR=0
Std Step Tol=0.01
Critical Tol=0.01
Num of Std Step Trials=20
Max Error Tol=0.3
Flow Tol Ratio=0.001
Split Flow NTrial=30
Split Flow Tol=0.02
Split Flow Ratio=0.02
Log Output Level=0
Friction Slope Method=1
Unsteady Friction Slope Method=2
Unsteady Bridges Friction Slope Method=1
Global Log Level=0
CheckData=False
Run HTab=0
Run UNet=0
Run PostProcess=0
UNET Theta=0
UNET Theta Warmup=0
UNET ZTol=0
UNET ZSATol=0
UNET MxIter=0
UNET MaxInSteps=0
UNET DtIC=0
UNET DtMin=0
UNET MaxCRTS=0
UNET WFStab=0
UNET SFStab=0
UNET WFX=0
UNET SFX=0
UNET DSS MLevel=0
UNET DZMax Abort=0
UNET Convert EG Bridges=0
UNET Use Existing IB Tables=0
UNET Froude Limit=0
UNET Froude Power=0
Write IC File=0
Echo Input=False
Echo Output=False
Write Detailed=0

--- BGRN.f01 (steady flow) ---

Flow Title=NFF Regression Equation
Program Version=4.10
Number of Profiles= 1
Profile Names=P100yr
River Rch & RM=BGRN,Main            ,4722.3
777.4276
River Rch & RM=BGRN,Main            ,3212
1065.444
River Rch & RM=BGRN,Main            ,588.1
1139.617
Boundary for River Rch & Prof#=BGRN,Main            , 1
Up Type= 0
Dn Type= 3
Dn Slope=0.0111
DSS Import GetInterval= 0
DSS Import GetPeak= 0
DSS Import FillOption= 0

--- BGRN.g01 (geometry) ---

Geom Title=USGS 10m DEM
Program Version=4.10

River Reach=BGRN            ,Main
Reach XY= 30
     1496606.296      266617.491      1496740.41      266565.408
     1496814.629      266482.074     1496949.297       266280.29
     1497069.128      266148.683     1497135.795      266127.155
     1497262.111      266118.359     1497354.993      266082.769
      1497648.96      265880.497     1497813.225      265876.612
     1497869.787      265858.748     1497920.135      265782.359
     1497936.628      265723.331     1498103.974      265530.705
     1498213.537      265363.522       1498400.7      265195.286
     1498655.871      264926.699     1498850.481      264504.832
     1498909.099      264293.431     1498914.552      264231.041
     1498890.707       264117.55     1498795.569      263943.592
     1498799.388      263830.745     1498730.985      263711.995
     1498710.499        263623.8     1498590.013      263475.536
     1498567.096       263260.97     1498546.503      263188.315
     1498586.888      263060.128     1498583.012      263002.451

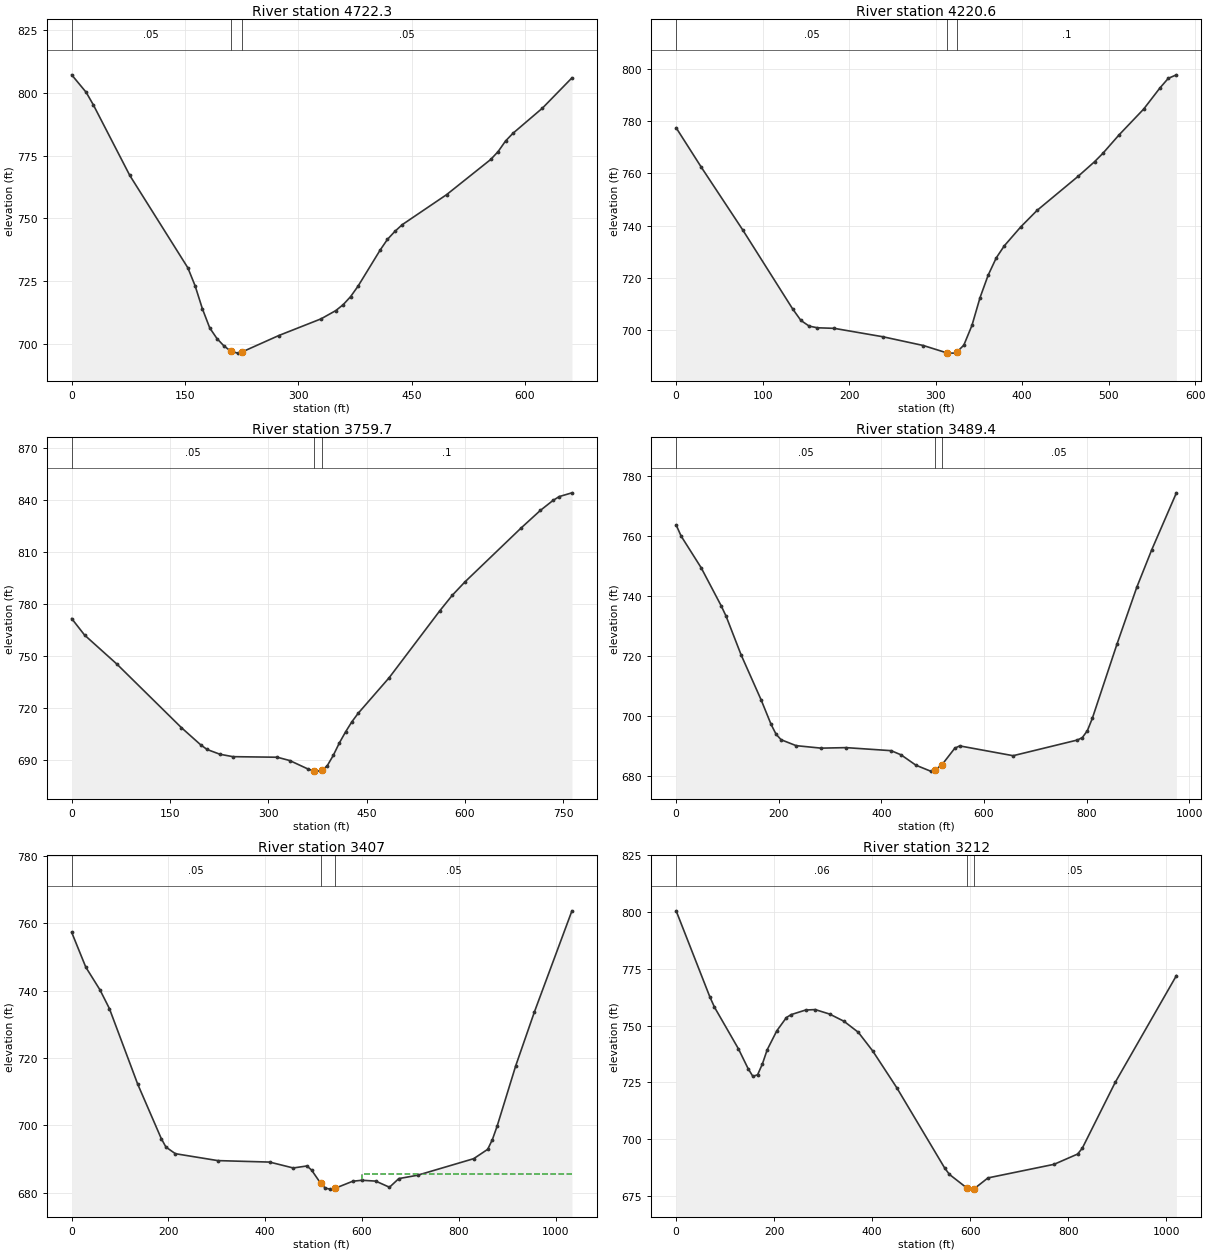
Type RM Length L Ch R = 1 ,4722.3  ,499.5,501.7,503.7
XS GIS Cut Line= 4
     1496884.073      266726.721     1496769.056      266572.642
     1496688.761      266485.836     1496393.622      266294.864
#Sta/Elev= 30
       0  807.12    19.2  800.16    28.8   795.1    76.9   767.1   153.8  730.32
   163.4  723.16     173  714.05   182.7  706.45   192.3   702.2   201.4  699.31
   210.5   697.2   219.6  696.41   225.5  696.87   274.1  703.41     330  710.04
   349.6  713.34   359.4  715.71   369.1  718.87   378.9     723   408.2  737.38
   417.9  741.66   427.7  744.82   437.5  747.51   496.1  759.43   554.6  773.45
   564.4  776.59   574.2  780.79   583.9  783.83     623  793.86   662.1  805.91
#Mann= 3 , 0 , 0
       0     .05       0   210.5    .045       0   225.5     .05       0
Bank Sta=210.5,225.5
XS Rating Curve= 0 ,0
Exp/Cntr=0.3,0.1

Type RM Length L Ch R = 1 ,4220.6  ,456.1,460.9,465.8
XS GIS Cut Line= 4
     1497250.393      266414.221     1497135.375      266260.142
     1497020.922      266112.066     1496875.089      265976.649
#Sta/Elev= 30
       0  777.38    28.8  762.46    76.9   738.4   134.6  708.23   144.2  703.79
   153.8  701.61   163.4  700.97   182.7  700.76   239.1  697.54   285.8   694.2
   313.1  691.37   313.9  691.29   323.3   691.3  325.16691.9045   332.6  694.33
     342  701.88   351.4  712.54   360.7  721.04   370.1  727.68   379.4  732.28
   398.4  739.51   417.3  745.82   464.7  758.82   483.7   764.4   493.2  767.56
   512.1  774.67   540.5  784.51   559.5  792.66     569  796.27   578.4  797.61
#Mann= 3 , 0 , 0
       0     .05       0   313.1    .045       0  325.16      .1       0
Bank Sta=313.1,325.16
XS Rating Curve= 0 ,0
Exp/Cntr=0.3,0.1

Type RM Length L Ch R = 1 ,3759.7  ,235.4,270.3,301.8
XS GIS Cut Line= 4
     1497538.283       266369.01     1497518.622       266084.36
     1497432.684      265904.673      1497273.83      265675.506
#Sta/Elev= 30
       0  771.57    19.7  762.02    68.9  745.28   167.3  708.58   196.8  698.61
   206.6  695.91   226.3  693.14     246  691.75   313.8  691.42   332.8   689.5
   361.2  684.51  370.02683.4702   370.7  683.39   380.2  683.53  382.26684.1347
   389.7  686.32   399.2  692.49   408.6  699.77   418.1  706.16   427.6  711.92
   437.1  716.78   484.5  737.39   561.4  775.89   580.7  784.98   599.9  792.67
   686.4  824.11   715.3   834.1   734.5  839.83   744.1  842.08   763.4  844.23
#Mann= 3 , 0 , 0
       0     .05       0  370.02    .045       0  382.26      .1       0
Bank Sta=370.02,382.26
XS Rating Curve= 0 ,0
Exp/Cntr=0.3,0.1

Type RM Length L Ch R = 1 ,3489.4  ,86.3,82.4,87.1
XS GIS Cut Line= 4
     1497552.476      266355.194     1497668.579      265912.268
     1497811.157      265773.596     1497630.601      265511.444
#Sta/Elev= 30
       0  763.61     9.7  759.91    48.7  749.37    87.7   736.7    97.4  733.19
   126.6  720.33   165.6  705.34   185.1  697.14   194.8  693.87   204.6  692.04
   233.8  690.07   282.5  689.24   331.2  689.41   418.9   688.4   438.4  687.01
   467.4  683.55   495.8  681.58   505.2     682  518.45683.7808   543.1  689.21
   552.6  689.99   656.8  686.72   782.2  691.95   791.8  692.78   801.5  695.05
   811.1  699.12   859.4  723.98   897.9  742.87   926.9   755.3   975.1  774.32
#Mann= 3 , 0 , 0
       0     .05       0   505.2    .045       0  518.45     .05       0
Bank Sta=505.2,518.45
XS Rating Curve= 0 ,0
Exp/Cntr=0.3,0.1

Type RM Length L Ch R = 1 ,3407    ,229.9,195,149.8
XS GIS Cut Line= 4
     1497618.448      266376.027     1497734.551      265933.102
     1497877.129       265794.43     1497685.289      265469.777
#Sta/Elev= 30
       0  757.31    29.2  746.96    58.4  740.24    77.9  734.69   136.4  712.25
   185.1  696.09   194.8  693.55   214.3  691.58     302  689.53   409.2  689.09
   457.9  687.34   486.3  687.94   495.8  686.72   514.7  682.77   524.2  681.37
   533.7  681.06   544.6  681.32     581  683.41     600  683.69   628.4  683.44
   656.8  681.62   676.1  684.19   714.8  685.18   830.8   690.1   859.8  692.88
   869.5  695.78   879.2  699.72   917.8  717.72   956.5  733.74  1033.9  763.69
#Mann= 3 , 0 , 0
       0     .05       0   514.7    .045       0   544.6     .05       0
#XS Ineff= 2 , 0
                          599.98          685.54
Permanent Ineff=
       F       F
Bank Sta=514.7,544.6
XS Rating Curve= 0 ,0
Exp/Cntr=0.3,0.1

Type RM Length L Ch R = 1 ,3212    ,528.3,530.5,532.4
XS GIS Cut Line= 4
     1498126.261      266322.208     1497967.407      265808.319
     1497885.809      265723.249     1497694.837      265412.485
#Sta/Elev= 30
       0   800.5    68.5  762.74    78.2  758.07   127.1  739.72   146.7  731.06
   156.5  727.61   166.2  728.33     176  733.13   185.8  739.36   205.4   747.7
   224.9   753.5   234.7  754.81     264  756.81   283.6  757.02     313  755.05
   342.3  751.88   371.6  747.02     401  738.79   449.9  722.67   547.7  687.28
   557.5  684.43   592.8   678.5   606.6  677.96   607.8   678.1   636.1   682.9
   770.9  688.88   818.9   693.4   828.5  695.98   895.7  724.98  1020.5  771.98
#Mann= 3 , 0 , 0
       0     .06       0   592.8    .045       0   607.8     .05       0
Bank Sta=592.8,607.8
XS Rating Curve= 0 ,0
Exp/Cntr=0.3,0.1

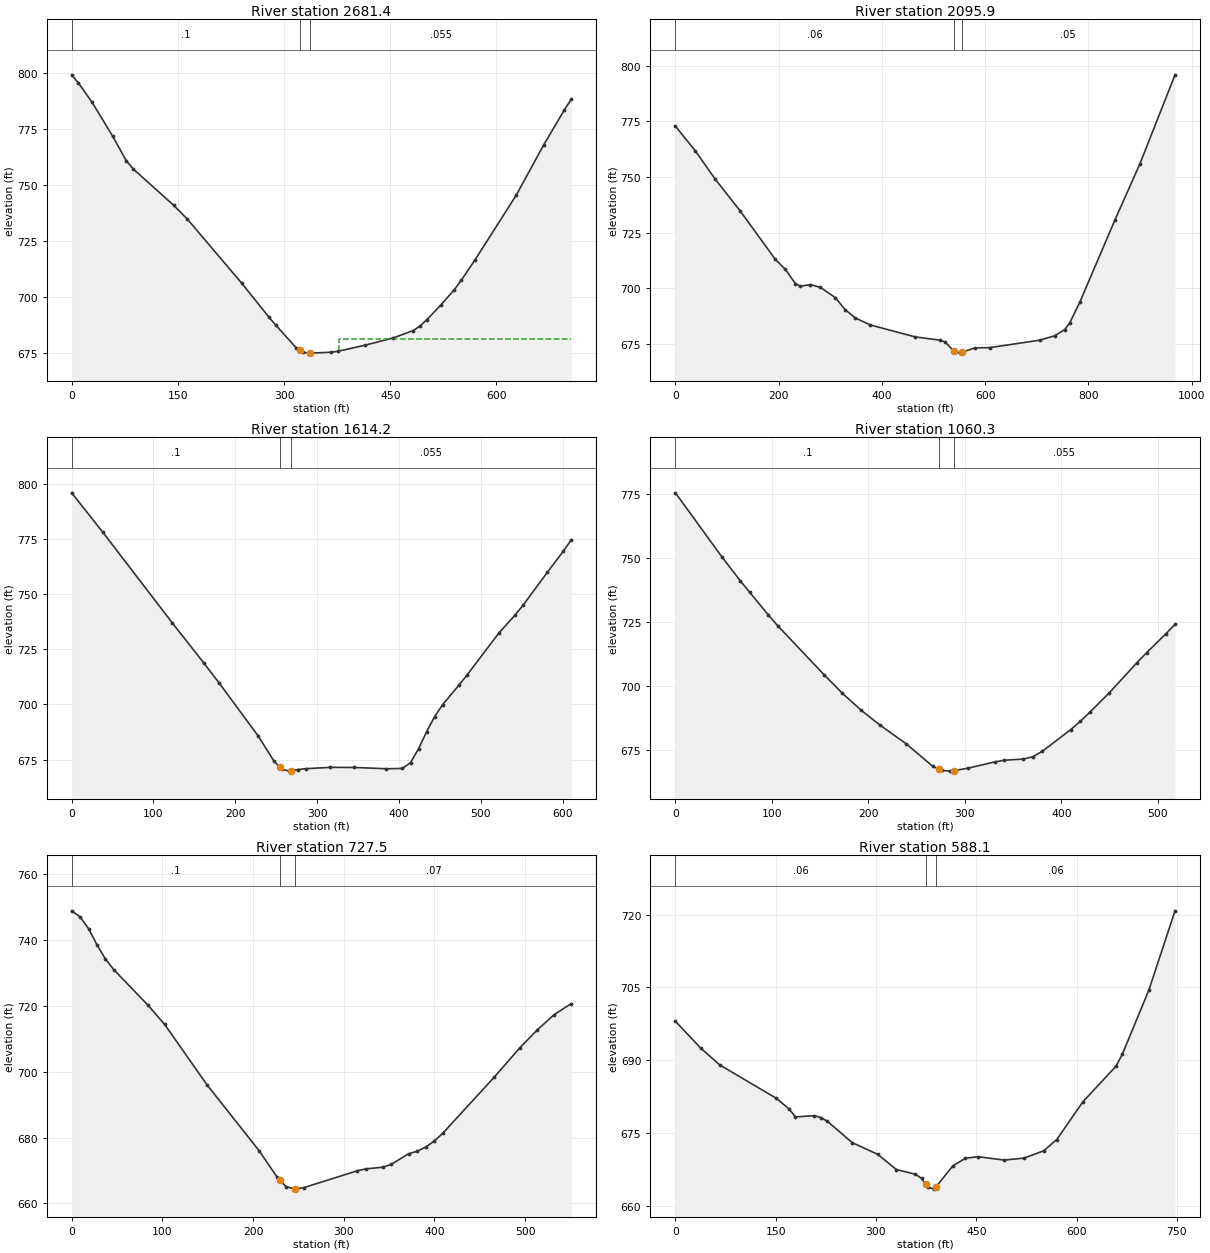
Type RM Length L Ch R = 1 ,2681.4  ,589.7,585.5,580.7
XS GIS Cut Line= 3
     1498420.966      265613.006     1498237.817      265342.063
     1498009.507       265040.09
#Sta/Elev= 30
       0  799.32     9.6  795.69    28.9  787.02    57.7  772.04      77     761
    86.6  757.35   144.3  740.95   163.5  734.79   240.5  706.05   278.9  690.89
   288.6  687.31   317.4  677.21   322.6  676.13     327  675.22   336.7  674.91
   365.9  675.29   375.6   675.7   414.4  678.46   453.2  681.61   482.4     685
     492  687.04   501.8  689.93   521.2  696.35   540.6  703.35   550.3  707.48
   569.7  716.61     628  745.58   666.8  768.08   695.9  783.66   705.6   788.4
#Mann= 3 , 0 , 0
       0      .1       0   322.6    .045       0   336.7    .055       0
#XS Ineff= 2 , 0
                          377.77           681.4
Permanent Ineff=
       F       F
Bank Sta=322.6,336.7
XS Rating Curve= 0 ,0
Exp/Cntr=0.3,0.1

Type RM Length L Ch R = 1 ,2095.9  ,488.4,481.7,474.6
XS GIS Cut Line= 4
     1499058.986      265298.336     1498698.743      264974.985
     1498607.598       264890.35     1498321.139      264673.336
#Sta/Elev= 30
       0  772.91    38.7  761.75    77.4  748.95   125.9  734.65   193.6  712.95
     213  708.47   232.4  702.08     242   700.9   261.4  701.59   280.8  700.38
   309.8  695.73   329.2  690.23   348.5   686.6   377.6  683.44   464.7  678.06
   512.8   676.6   522.4  675.82   539.3  671.66     551  670.77   554.3  671.07
   579.8  673.14   608.5  673.24   705.6  676.59   734.7  678.59   754.2  681.39
   763.9  684.43   783.3  693.66   851.3  730.65   899.8  755.97   967.8     796
#Mann= 3 , 0 , 0
       0     .06       0   539.3    .045       0   554.3     .05       0
Bank Sta=539.3,554.3
XS Rating Curve= 0 ,0
Exp/Cntr=0.3,0.1

Type RM Length L Ch R = 1 ,1614.2  ,564.1,553.9,542.7
XS GIS Cut Line= 3
     1499087.251      264607.785     1498882.363      264508.904
     1498535.983      264345.645
#Sta/Elev= 30
       0  795.79    37.9  778.03   123.2  736.78   161.2  718.87   180.1  709.74
   227.5  685.89   247.1  674.36   254.4671.5117     257   670.5   266.8  669.76
   267.4   669.8   276.6  670.47   286.4  670.88   315.9  671.46   345.3  671.42
   384.6  670.84   404.2  670.98     414  673.58   423.9  679.93   433.7   687.6
   443.5  694.47   453.3  699.91     473  708.62   482.8  713.16   522.1  732.38
   541.7  740.41   551.5  744.88     581  759.72   600.6  769.32   610.4  774.47
#Mann= 3 , 0 , 0
       0      .1       0   254.4    .045       0   267.4    .055       0
Bank Sta=254.4,267.4
XS Rating Curve= 0 ,0
Exp/Cntr=0.3,0.1

Type RM Length L Ch R = 1 ,1060.3  ,336.6,332.8,327
XS GIS Cut Line= 4
     1499091.539      263970.211     1498870.184      263972.381
      1498770.36      263976.738     1498574.908      263998.355
#Sta/Elev= 30
       0  775.33    48.1  750.41    67.4  740.97      77  736.55    96.2  727.77
   105.9  723.57     154  704.45   173.2  697.14   192.5  690.58   211.7  684.87
   239.5  677.41   266.8  668.69   273.6  667.51   275.9  667.11     285  666.82
   288.6     667   303.1  667.96   331.1  670.42     341  671.07   360.6  671.53
   370.4  672.41   380.3  674.55   409.8  683.01   419.6  686.19   429.4  689.71
   449.1  697.11   478.6  709.16   488.4  712.98   508.1  720.24   517.9  724.05
#Mann= 3 , 0 , 0
       0      .1       0   273.6    .045       0   288.6    .055       0
Bank Sta=273.6,288.6
XS Rating Curve= 0 ,0
Exp/Cntr=0.3,0.1

Type RM Length L Ch R = 1 ,727.5   ,138.8,139.4,139.2
XS GIS Cut Line= 4
     1498941.799      263722.815     1498789.889      263651.201
      1498637.98      263688.093     1498522.962      263883.405
#Sta/Elev= 30
       0  748.78     9.3  746.97    18.7  743.36      28  738.44    37.3  734.13
    46.6   730.9      84   720.2   102.6  714.31   149.3  695.98     207  675.91
   226.6  667.96   229.7  667.06   236.3  665.14   246.1  664.35  246.71 664.378
   255.9   664.8   314.5  669.88   324.3   670.5   343.2     671   352.6  671.89
   371.5  675.09   380.9  675.83   390.4  677.11   399.8  678.93   409.3  681.32
   465.9   698.3   494.3  707.26   513.2  712.59     532  717.28   550.9  720.64
#Mann= 3 , 0 , 0
       0      .1       0   229.7    .045       0  246.71     .07       0
Bank Sta=229.7,246.71
XS Rating Curve= 0 ,0
Exp/Cntr=0.3,0.1

Type RM Length L Ch R = 1 ,588.1   ,59.1,60.3,60.5
XS GIS Cut Line= 5
     1499006.903      263612.138     1498848.483      263527.503
     1498707.424      263539.438     1498580.471      263573.076
     1498308.118      263685.923
#Sta/Elev= 30
       0  698.02    37.8  692.49    66.2  689.03   151.2  682.12   170.2  679.92
   179.6  678.31   207.9  678.56   217.4  678.18   226.8  677.46   264.6     673
   302.3  670.62   330.6  667.46   358.7  666.52   368.1  665.64   374.3  664.47
   377.5  663.86   386.8  663.43   389.3  663.82     415  668.23   433.8  669.79
   452.5  670.11   491.8  669.42   521.3  669.82   550.8  671.32   570.4  673.65
   609.7  681.46   658.9  688.74   668.7   691.3     708  704.38   747.3  720.77
#Mann= 3 , 0 , 0
       0     .06       0   374.3    .045       0   389.3     .06       0
Bank Sta=374.3,389.3
XS Rating Curve= 0 ,0
Exp/Cntr=0.3,0.1

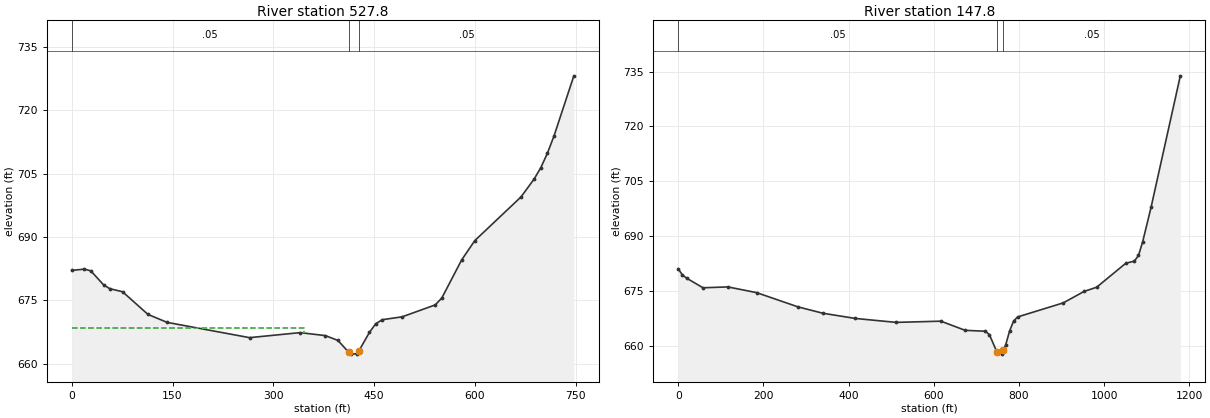
Type RM Length L Ch R = 1 ,527.8   ,368.7,380,389.5
XS GIS Cut Line= 5
     1499004.733        263556.8     1498846.313      263472.164
     1498705.254        263484.1     1498578.301      263517.737
     1498305.948      263630.584
#Sta/Elev= 30
       0  682.07    18.9  682.38    28.4  681.96    47.3  678.66    56.7  677.74
    75.6  677.02   113.4  671.66   141.8  669.78   264.6  666.16   339.9  667.35
   377.5  666.64   396.2   665.5   412.4  662.67     415  662.26   424.4  662.35
   427.4  663.03   443.1  667.42   452.5  669.47   462.3  670.41   491.8  671.09
     541  673.91   550.8  675.55   580.3  684.55   599.9  689.13   668.7  699.47
   688.4  703.75   698.2  706.41     708  709.82   717.8   713.9   747.3  728.12
#Mann= 3 , 0 , 0
       0     .05       0   412.4    .045       0   427.4     .05       0
#XS Ineff= 2 , 0
          345.59   668.5
Permanent Ineff=
       F       F
Bank Sta=412.4,427.4
XS Rating Curve= 0 ,0
Exp/Cntr=0.3,0.1

Type RM Length L Ch R = 1 ,147.8   ,154.5,147.8,139.6
XS GIS Cut Line= 5
     1499163.804      263549.855      1498948.49       263287.79
     1498674.221      263174.855     1498481.513      263124.508
     1498139.499      263089.786
#Sta/Elev= 30
       0     681     9.7  679.37    19.4  678.48    58.1  675.83   116.3  676.07
   184.1   674.5     281  670.61   339.2  668.87   415.7  667.44   511.4  666.36
   616.6  666.69   673.7  664.18   721.2  663.94   730.6  662.98   748.2  658.23
   759.1  657.67   763.2  658.74   768.6  660.14     778  664.04   787.5  666.76
     797  667.86   903.7  671.69   952.8  674.83   982.3  675.98    1051  682.57
  1070.7  683.11  1080.5  684.67  1090.3  688.41    1110  697.84  1178.7  733.85
#Mann= 3 , 0 , 0
       0     .05       0   748.2    .045       0   763.2     .05       0
Bank Sta=748.2,763.2
XS Rating Curve= 0 ,0
Exp/Cntr=0.3,0.1

Chan Stop Cuts=-1
Use User Specified Reach Order=0
Composite Channel Slope=5